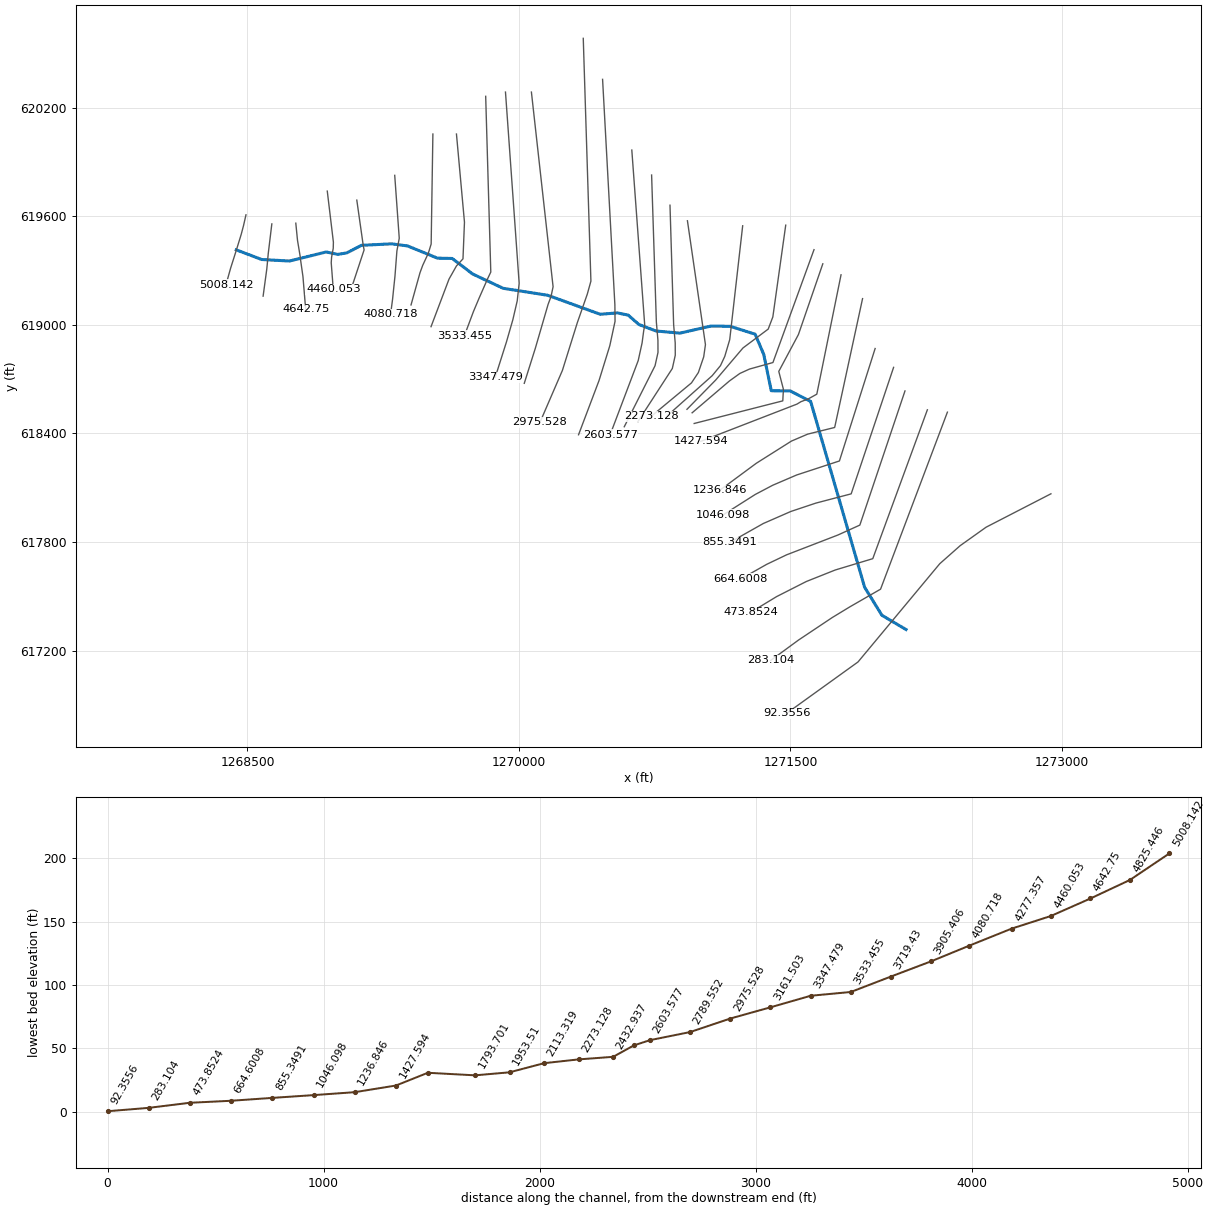
--- 527_ras.prj (project) ---

Proj Title=527
Current Plan=p01
Default Exp/Contr=0.3,0.1
English Units
Geom File=g01
Flow File=f01
Plan File=p01
Y Axis Title=Elevation
X Axis Title(PF)=Main Channel Distance
X Axis Title(XS)=Station
BEGIN DESCRIPTION:
RFD model 527 exported to HEC-RAS
END DESCRIPTION:

--- 527_ras.p01 (plan) ---

Plan Title=Plan 01
Program Version=4.10
Short Identifier=Plan 01
Geom File=g01
Flow File=f01
Subcritical Flow
Calc Critical at every XS
Secant Critical Depth

--- 527_ras.f01 (steady flow) ---

Flow Title=Flow 01
Program Version=5.01
Number of Profiles= 5
Profile Names=10yr,25yr,50yr,100yr,500yr
River Rch & RM=527,29,5008.142
  381.72  454.99  542.33  577.99  677.05
River Rch & RM=527,29,4080.718
  400.62   480.9  574.13  616.26  728.53
River Rch & RM=527,29,3905.406
  403.09   484.3  578.31  621.32  735.36
River Rch & RM=527,29, 3719.43
  419.78  507.36  606.66   655.7  782.05
River Rch & RM=527,29,3533.455
  422.85  511.61  611.89  662.06  790.73
River Rch & RM=527,29,3347.479
  447.64  546.13  654.41  714.07  862.12
River Rch & RM=527,29,3161.503
  454.55   555.8  666.33  728.72  882.37
River Rch & RM=527,29,2975.528
  458.61   561.5  673.37  737.39  894.37
River Rch & RM=527,29,2789.552
  461.96   566.2  679.17  744.54  904.29
River Rch & RM=527,29,2603.577
  464.61  569.92  683.76  750.21  912.17
River Rch & RM=527,29,2432.937
  479.42  590.79  709.54  782.12  956.65
River Rch & RM=527,29,2273.128
  485.03  598.72  719.34  794.29  973.68
River Rch & RM=527,29,2113.319
  495.36  613.36  737.45  816.82 1005.31
River Rch & RM=527,29, 1953.51
  499.52  619.27  744.76  825.94 1018.14
River Rch & RM=527,29,1793.701
  504.79  626.77  754.04  837.53 1034.49
River Rch & RM=527,29,1575.158
  515.09  641.44  772.21  860.28 1066.67
River Rch & RM=527,29,1427.594
  517.89  645.45  777.17   866.5 1075.49
River Rch & RM=527,29,1236.846
  533.19  667.34  804.31  900.63 1124.04
River Rch & RM=527,29,1046.098
  573.08  724.87  875.74  991.13 1254.04
River Rch & RM=527,29,855.3491
  577.83  731.76  884.31 1002.06 1269.85
River Rch & RM=527,29,664.6008
  600.75  765.12  925.81 1055.14 1347.02
River Rch & RM=527,29,473.8524
  621.55  795.56  963.74 1103.91 1418.41
River Rch & RM=527,29, 283.104
  707.99  923.61  1123.7 1312.17 1728.17
River Rch & RM=527,29, 92.3556
  709.02  925.16 1125.64 1314.72 1732.01
Boundary for River Rch & Prof#=527,29,1
Up Type= 0
Dn Type= 2
Boundary for River Rch & Prof#=527,29,2
Up Type= 0
Dn Type= 2
Boundary for River Rch & Prof#=527,29,2
Up Type= 0
Dn Type= 2
Boundary for River Rch & Prof#=527,29,2
Up Type= 0
Dn Type= 2
Boundary for River Rch & Prof#=527,29,2
Up Type= 0
Dn Type= 2

--- 527_ras.g01 (geometry) ---

Geom Title=527
Program Version=4.10

River Reach=527,29
Reach XY= 30
1268438.16868943619414.4318033011268579.00197962 619361.09848167
1268732.33526745619352.7651463151268934.83520913619402.765125558
1268999.00185657619389.4317943011269049.00184196 619397.76512371
1269129.83515275619439.4317756441269297.33510351619447.765101597
1269384.83507735619436.0984358191269549.83502662619368.598451048
 1269631.5016692619366.931782484 1269744.0016335619281.098471329
1269913.16824791619201.9318231941270159.00150755619163.598494053
1270449.00141895619058.5985167771270544.00139102619066.098511755
1270603.61650425619053.7298316961270662.88914305619002.038629159
1270757.29018474618966.231337517  1270889.001286618954.431868151
1271061.50123626618993.5985181331271167.33453828618991.931848854
1271304.83449644618948.5985243471271352.33447912618836.931889474
 1271394.0011276618636.0986145291271498.25661993618635.437066659
1271611.50106168618576.9319590481271909.83427688617550.265588522
1272004.83424431617396.0989648251272138.16753602617316.932317764

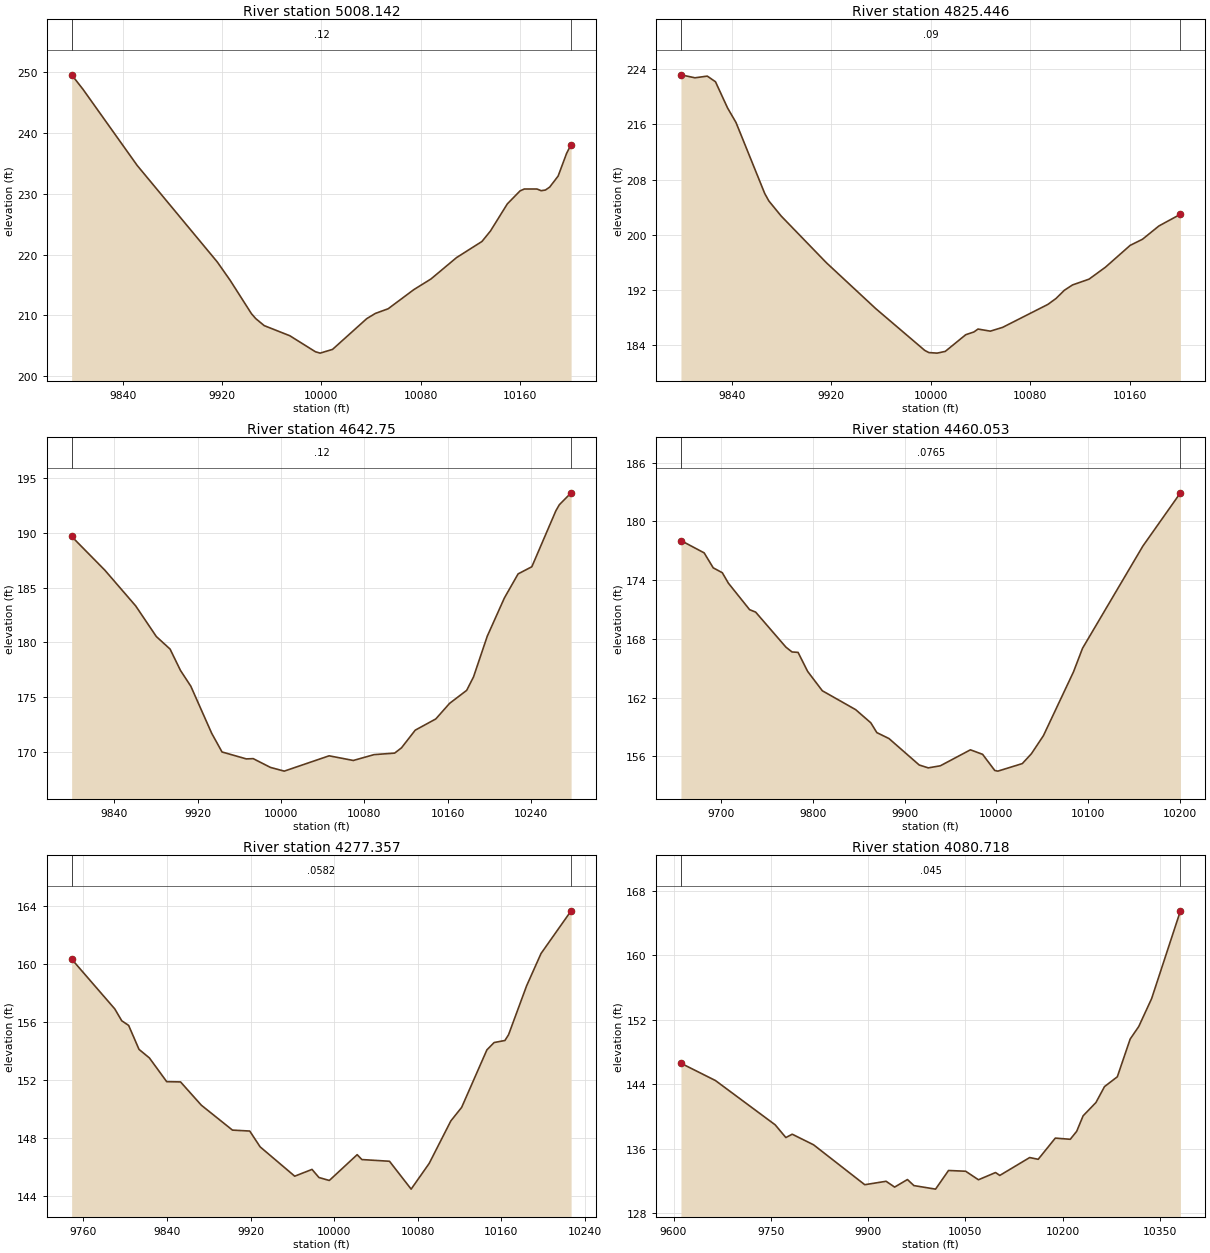
Type RM Length L Ch R = 1 ,5008.142,182.696300,182.696300,182.696300
XS GIS Cut Line= 6
1268491.90948048 619607.942807241268478.63723416619549.338914817
 1268465.0156897619498.0843952431268439.43030659619415.070804142
1268406.99224786619313.0162290131268381.44778574619221.612746747
#Sta/Elev= 30
9799.011249.53729808.046247.18529851.777234.63959916.256218.76939926.555215.7703
9943.721210.27619947.154209.4708 9954.02208.31019974.619206.64869995.218204.0174
    9999203.792110008.98204.405310036.52209.462410043.41210.314610053.73211.0837
10074.39214.227410088.16215.974310108.78219.493710129.22222.142810136.04223.8537
10149.66228.323410159.88230.455310163.29230.770610173.51230.768310176.91230.4896
10180.32230.603710183.73231.078910190.54232.894310197.35 236.62210200.99238.0781
#Mann= 3 , 0 , 0
9799.011    0.12       09799.011    0.12       010200.99    0.12       0
#XS Ineff= 2 , 0
       0                               0
Bank Sta=9799.011,10200.99
Exp/Cntr=0.3,0.1

Type RM Length L Ch R = 1 ,4825.446,182.696400,182.696400,182.696400
XS GIS Cut Line= 6
1268634.76367477619557.8151372341268614.80467097619392.517744891
1268611.77055887619359.1651777671268611.62806471619357.170260371
1268606.92554212619308.6902193081268586.63529784619158.771186091
#Sta/Elev= 30
9799.012223.1815 9810.27222.74979820.184222.99499826.794222.17789836.496218.3862
9843.317216.2695 9866.45 205.9759869.754204.90199879.668202.71799916.019195.9565
9955.675189.31729995.239183.24239998.533182.934510005.12182.852310011.71183.1019
10028.19185.519310034.79185.921110038.08 186.34110047.97186.0367 10057.9186.5871
10094.31189.911910100.94190.783410107.56191.961810114.18192.737410127.42193.5711
10140.67195.309110160.53198.468910170.46199.3545 10183.7201.285410200.99202.9745
#Mann= 3 , 0 , 0
9799.012    0.09       09799.012    0.09       010200.99    0.09       0
#XS Ineff= 2 , 0
       0                10040.44       0
Bank Sta=9799.012,10200.99
Exp/Cntr=0.3,0.1

Type RM Length L Ch R = 1 , 4642.75,182.696400,182.696400,182.696400
XS GIS Cut Line= 6
1268767.22177929619561.9185516691268776.55038321619467.513938501
1268791.20261449619379.2388491631268793.15390277619361.727438927
  1268806.662343619267.281473234  1268821.711481619085.845052794
#Sta/Elev= 30
9799.032189.65549830.871186.58379860.542183.31869880.323180.52789893.511179.3843
9903.484177.44039913.462175.99089933.416171.71259943.393169.99849966.673 169.367
9973.324169.39059989.907168.589110003.12168.2518 10046.2169.6487 10069.4169.2239
10089.29169.755910109.09 169.89510115.67170.379410128.84171.987810148.59173.0116
10161.76 174.42710178.22175.619510184.81176.849610197.98180.557810214.44  184.05
 10227.6186.240810240.77186.893410263.82191.992410267.11192.542610278.47193.6349
#Mann= 3 , 0 , 0
9799.032    0.12       09799.032    0.12       010278.47    0.12       0
#XS Ineff= 2 , 0
       0                10051.14       0
Bank Sta=9799.032,10278.47
Exp/Cntr=0.3,0.1

Type RM Length L Ch R = 1 ,4460.053,182.696300,182.696300,182.696300
XS GIS Cut Line= 6
 1268941.0691199619739.0568583461268974.87386563619457.020407408
1268974.03187507619423.0400010651268964.90399122619373.990520373
1268962.89760908619343.0152451991268974.12886956619197.432894215
#Sta/Elev= 30
9655.885178.0403 9681.18176.7847  9691.1175.25289701.021174.75499707.634173.6879
9730.781170.97939737.395170.72839770.463167.14349777.076166.6577 9783.69 166.612
9794.167164.66299810.144162.69159846.518160.76099863.052159.41639869.666158.4124
9882.893157.80539915.902155.10179925.775154.80879938.938155.02149971.759156.6536
9985.048156.19379998.369154.540910001.74154.476110028.39155.246310038.26156.2465
10051.41158.095910084.25164.6214 10094.1167.029710159.98177.481110200.96182.9213
#Mann= 3 , 0 , 0
9655.885  0.0765       09655.885  0.0765       010200.96  0.0765       0
#XS Ineff= 2 , 0
       0                10041.54       0
Bank Sta=9655.885,10200.96
Exp/Cntr=0.3,0.1

Type RM Length L Ch R = 1 ,4277.357,196.638600,196.638600,196.638600
XS GIS Cut Line= 4
1269104.16518471619689.2782125171269139.76939595619438.683528289
1269144.50091171619414.2698770611269081.59574029619224.000434741
#Sta/Elev= 30
9748.648160.32189789.994156.88319796.621156.06819803.249155.7456 9813.19154.0928
9823.131153.5033  9839.7 151.8679852.955151.84969872.838150.24529902.662148.5256
9919.231148.46039929.172147.3705 9962.31145.34679978.879145.81429985.507 145.256
9995.448145.050910022.13146.830810026.63146.493410053.08146.376510073.81144.4542
10091.09146.226910111.82 149.15710122.19150.093810146.37154.059610153.29 154.565
10163.65154.707610167.11155.104410184.38158.473210198.21160.705210227.03163.6506
#Mann= 3 , 0 , 0
9748.648  0.0582       09748.648  0.0582       010227.03  0.0582       0
#XS Ineff= 2 , 0
       09951.338        10109.47       0
Bank Sta=9748.648,10227.03
Exp/Cntr=0.3,0.1

Type RM Length L Ch R = 1 ,4080.718,175.312700,175.312700,175.312700
XS GIS Cut Line= 6
1269313.68196711619826.0794278091269338.68363172619478.750780374
1269325.69738027619407.9831509441269315.09821334619269.602091983
1269301.58200109619139.7335591171269290.94676873619059.684900522
#Sta/Elev= 30
9611.438146.61659664.639144.4693 9756.74138.97199773.187137.39149783.055137.8054
9815.948136.49039894.892131.53539927.785 131.9599940.943131.23879960.692132.1758
9970.688131.425610004.07130.985910024.08133.301210050.51133.206610070.25132.1474
10096.57133.046110103.16132.686510149.22134.907610162.38134.690610188.75137.3211
10211.84137.174910221.74138.165610231.63140.088810251.42141.740110264.62143.7158
10284.41144.937210304.21149.621710317.45 151.18110337.31154.649510381.74165.5462
#Mann= 3 , 0 , 0
9611.438   0.045       09611.438   0.045       010381.74   0.045       0
#XS Ineff= 2 , 0
       09923.356        10043.69       0
Bank Sta=9611.438,10381.74
Exp/Cntr=0.3,0.1

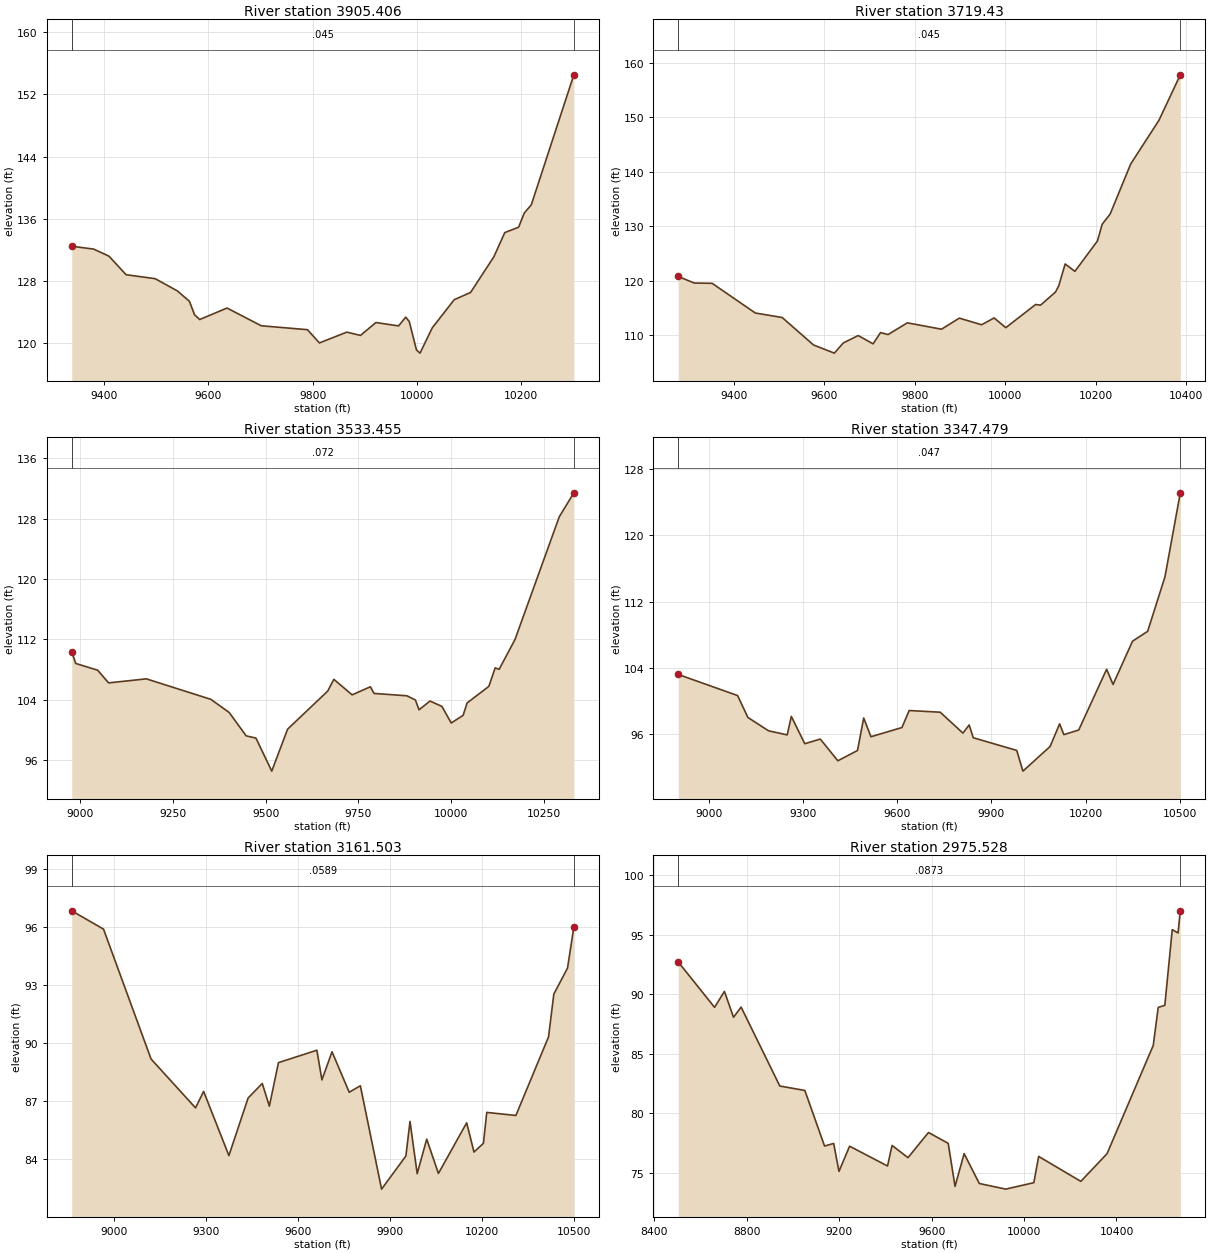
Type RM Length L Ch R = 1 ,3905.406,185.975600,185.975600,185.975600
XS GIS Cut Line= 6
1269524.53266156620054.3780388831269514.98405048619446.739150017
1269499.31568369619395.740446046 1269468.2805554619328.820202872
 1269453.1929175619287.6724731771269403.78639475619110.199143708
#Sta/Elev= 30
9337.935 132.4719379.802132.10439409.333131.19139442.145128.80919497.926128.2981
9540.583126.71899563.551125.39489573.395123.66929583.239 123.0469635.738124.5193
9701.363122.24099789.957121.73759812.925120.03429865.425 121.4249891.675     121
9921.206122.6562  9964.7122.22379978.429123.35149985.293122.7732    9999 119.134
10005.87118.722710029.28121.971410071.35125.589910102.85126.528810147.52131.1181
10168.41134.224710194.98 134.92110205.76136.734810219.33137.807510300.86154.5168
#Mann= 3 , 0 , 0
9337.935   0.045       09337.935   0.045       010300.86   0.045       0
#XS Ineff= 2 , 0
       09952.161         10059.3       0
Bank Sta=9337.935,10300.86
Exp/Cntr=0.3,0.1

Type RM Length L Ch R = 1 , 3719.43,185.975600,185.975600,185.975600
XS GIS Cut Line= 6
1269654.74099493620054.3780388831269699.01182824619567.398872226
1269690.76530048619364.7079000171269654.76947725 619325.71973604
1269613.66604531619252.9199713321269514.28055951618990.014578551
#Sta/Elev= 30
9276.821 120.7839312.267119.57629351.799119.52359447.336114.07919506.634113.2584
9575.816108.22879621.937106.72929641.703108.59679674.647109.9514 9707.59 108.433
9724.062110.49269740.534110.12859783.303112.27859858.824111.11689898.227113.1434
 9947.48 111.9329975.223113.1798   10001111.3965 10066.9115.639910077.91 115.531
 10110.8117.923610117.95119.052310132.25123.0723 10153.7121.719810203.46127.2719
10214.04130.353410231.67132.227210277.09141.396310339.63149.421510386.77157.7435
#Mann= 3 , 0 , 0
9276.821   0.045       09276.821   0.045       010386.77   0.045       0
#XS Ineff= 2 , 0
       09966.044        10065.98       0
Bank Sta=9276.821,10386.77
Exp/Cntr=0.3,0.1

Type RM Length L Ch R = 1 ,3533.455,185.975600,185.975600,185.975600
XS GIS Cut Line= 6
1269816.19932827620262.7113722411269844.43288416 619291.80136922
1269827.84315386 619256.977303431269780.03116927619148.221772969
1269748.56200099 619073.477017031269698.10520372618938.961325362
#Sta/Elev= 30
8977.371110.3585 8988.07108.80379047.149107.91169076.689106.22829178.438106.7631
9352.396104.04519401.629102.3096 9447.5899.206269473.83898.910769516.50794.52974
9559.176100.09059667.489105.1469  9683.9106.70199733.134104.64259782.367105.7131
9792.213104.83049880.833104.51729903.809103.95689913.656102.66539943.196103.8214
9975.313103.108710000.32100.907910032.37101.926810043.19103.569510101.76105.7675
10118.79 108.21710129.47108.025110172.19111.971610291.56128.241210330.88131.4253
#Mann= 3 , 0 , 0
8977.371   0.072       08977.371   0.072       010330.88   0.072       0
#XS Ineff= 2 , 0
       09953.343           10059       0
Bank Sta=8977.371,10330.88
Exp/Cntr=0.3,0.1

Type RM Length L Ch R = 1 ,3347.479,185.975600,185.975600,185.975600
XS GIS Cut Line= 6
1269925.57432827620286.1488722411270001.12917522619229.793845981
1269990.49368411619132.9107255041269966.37904856619028.858579054
1269930.99427471 618905.98209928 1269868.6076428618709.444908425
#Sta/Elev= 30
8903.511103.21849092.323100.67259125.21598.028479190.99996.416949250.205  95.928
9263.362   98.169306.12294.86382 9355.4695.421639411.37792.803989473.87294.04274
9493.60797.967759516.63195.703499615.30896.815619638.33298.866889737.009 98.6637
9809.37296.141459829.10797.123419842.26495.581849980.45594.0522810000.2491.55509
10086.6694.5280910116.9797.2554210130.45 95.959310177.7496.5157410266.51103.8436
10286.99102.011710348.89107.229310397.08108.423110452.15115.002410500.95 125.132
#Mann= 3 , 0 , 0
8903.511   0.047       08903.511   0.047       010500.95   0.047       0
#XS Ineff= 2 , 0
       09951.182        10068.63       0
Bank Sta=8903.511,10500.95
Exp/Cntr=0.3,0.1

Type RM Length L Ch R = 1 ,3161.503,185.975600,185.975600,185.975600
XS GIS Cut Line= 6
 1270068.8034949620286.1488722411270188.59516156619210.628038883
1270177.23205772  619156.80450661270160.99028116 619113.17815949
1270090.45242831618870.6471200291270029.41183752618677.219535142
#Sta/Elev= 30
8861.81996.851738965.48595.905149120.63889.185569265.88786.654169292.29687.50815
9374.82484.185049437.54587.165849483.76187.917789506.869 86.74369536.57988.99599
9662.02289.638249678.52788.102969711.53889.556249767.65887.46257 9803.9787.79934
9873.29382.450359952.65584.164819966.06785.954759989.53983.2509310020.6585.03635
10058.8283.2619210151.07 85.881410174.9984.3694110205.7484.8207610216.6686.41986
10311.7586.26262 10418.490.33087 10435.692.5418910480.3393.8890710500.9796.01168
#Mann= 3 , 0 , 0
8861.819  0.0589       08861.819  0.0589       010500.97  0.0589       0
#XS Ineff= 2 , 0
       09949.523        10102.16       0
Bank Sta=8861.819,10500.97
Exp/Cntr=0.3,0.1

Type RM Length L Ch R = 1 ,2975.528,185.975600,185.975600,185.975600
XS GIS Cut Line= 6
1270355.26182827620583.0238722411270397.53988853619241.848987684
1270377.62412116619170.0443542751270322.30011368 619011.61494939
1270239.95084897618748.1742020251270116.11252266 618461.49609445
#Sta/Elev= 30
8503.67492.718178660.87488.897168703.546 90.24098742.93688.063918775.76188.91945
8943.16682.278879051.48881.907079136.83277.229389176.22177.449779199.19875.09748
9245.15377.216459409.27675.551879428.97177.280149497.90376.253929586.52978.37111
9671.87377.456189701.41573.835899740.805 76.59099806.45474.078859920.76873.60571
10042.32 74.147510063.2276.3561210245.7274.2586110359.16 76.5869 10559.185.69492
10580.55  88.89310609.14 89.0722 10641.395.4367110666.3295.1573310676.1697.01865
#Mann= 3 , 0 , 0
8503.674  0.0873       08503.674  0.0873       010676.16  0.0873       0
#XS Ineff= 2 , 0
       09923.231        10082.65       0
Bank Sta=8503.674,10676.16
Exp/Cntr=0.3,0.1

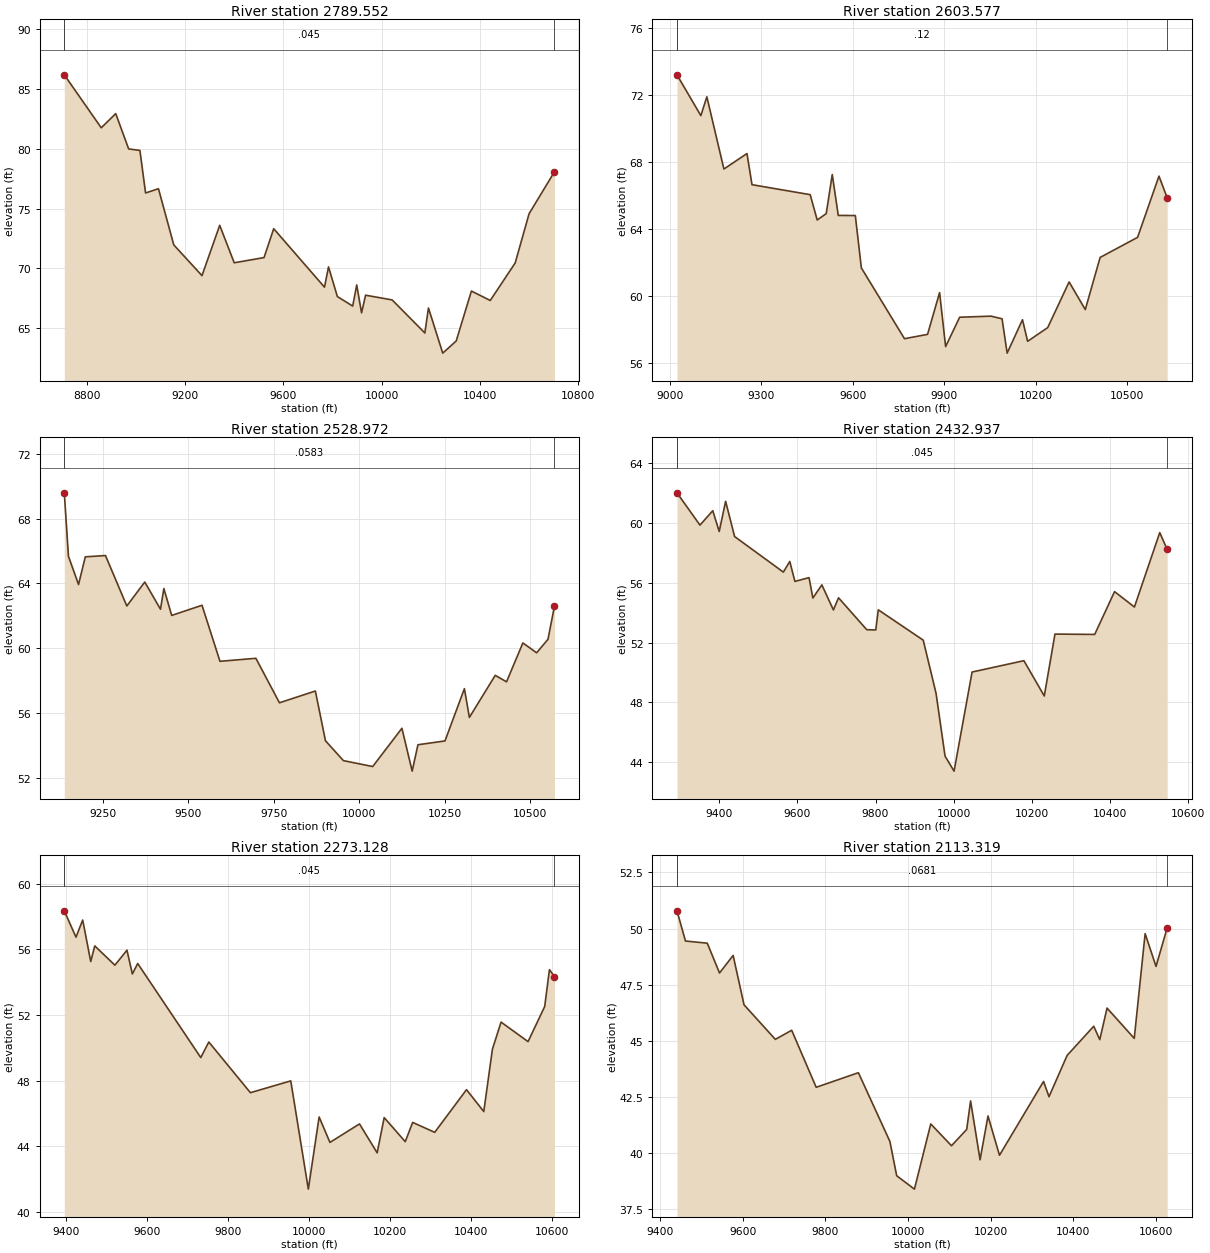
Type RM Length L Ch R = 1 ,2789.552,185.975600,185.975600,185.975600
XS GIS Cut Line= 6
1270462.03266159620356.4613722411270529.96277091619110.677274466
1270530.88965696619019.6121325491270501.85865438618884.691641524
  1270442.456734618692.6099101011270329.22016156 618392.91970557
#Sta/Elev= 30
8706.82686.159318857.425 81.73918916.56882.922458969.13979.976649015.13979.84949
9038.13976.30067 9090.71 76.65449153.13971.969219268.13869.402349340.42473.60031
9399.56770.474839521.13870.909179560.56673.318269767.56668.441349783.99570.12994
9820.13767.655379882.56666.862339898.99468.624149918.70866.297829935.137 67.7709
10043.4867.3751410176.7664.6174710191.4566.7011710249.6762.9360310304.5563.94883
10366.5668.1163210443.3967.33001 10545.170.4640510601.6374.5652810705.2178.07145
#Mann= 3 , 0 , 0
8706.826   0.045       08706.826   0.045       010705.21   0.045       0
#XS Ineff= 2 , 0
       09938.761        10098.32       0
Bank Sta=8706.826,10705.21
Exp/Cntr=0.3,0.1

Type RM Length L Ch R = 1 ,2603.577,74.605100,74.605100,74.605100
XS GIS Cut Line= 6
 1270623.4909949619965.8363722261270694.94638237618996.933844864
1270689.36317912618968.617906302 1270680.1322507618899.618761539
1270658.82666078618802.7153931111270503.69932824 618392.91970557
#Sta/Elev= 30
9023.49973.204529101.70570.764319121.44471.889999177.371 67.57159253.037 68.4962
9269.486 66.63499460.29566.037569483.32464.522059512.93364.904259532.67267.24001
 9552.41 64.79619608.337 64.78889628.07661.657449769.53957.423739845.20457.68296
9884.67760.181759904.41356.950219950.46358.7077510053.0958.77213 10089.558.61569
10106.1656.5610410156.4958.5580310173.3657.2674910239.2458.08848 10309.460.81828
10362.3959.1656810411.14 62.284310533.9263.4843610604.0867.1461610630.9365.85225
#Mann= 3 , 0 , 0
9023.499    0.12       09023.499    0.12       010630.93    0.12       0
#XS Ineff= 2 , 0
       09942.543        10064.05       0
Bank Sta=9023.499,10630.93
Exp/Cntr=0.3,0.1

Type RM Length L Ch R = 1 ,2528.972,96.034200,96.034200,96.034200
XS GIS Cut Line= 6
 1270732.8659949619827.8155388981270759.06731197619016.447705969
1270767.80039927618915.2202235311270768.14380732618847.699132472
 1270751.8359023618774.2608514131270581.82432824618437.190538898
#Sta/Elev= 30
9136.88969.601479149.04665.682499178.59263.93599 9198.2965.647299257.38265.72583
9319.75862.609679372.28464.090339418.245 62.40939428.09463.687059451.07462.02696
9539.71362.65365 9592.2459.192189697.29359.377889766.234 56.62939871.287 57.3571
9900.83454.283669953.355 53.056610038.9852.6909810124.4355.0549110154.44 52.4075
10171.3654.0371110250.4254.2727610307.2257.5020610321.7955.72588 10397.458.32429
10430.4757.9251710478.24 60.327210518.4959.7179210551.7360.5541310570.6962.60401
#Mann= 3 , 0 , 0
9136.889  0.0583       09136.889  0.0583       010570.69  0.0583       0
#XS Ineff= 2 , 0
       09946.929        10042.45       0
Bank Sta=9136.889,10570.69
Exp/Cntr=0.3,0.1

Type RM Length L Ch R = 1 ,2432.937,159.809200,159.809200,159.809200
XS GIS Cut Line= 6
1270834.42849493619661.1488722261270854.55342308619001.256733745
1270863.28651035618900.0292512921270863.62991843618832.508160233
1270847.32201341618759.0698791741270657.34516156618465.836372226
#Sta/Elev= 30
9292.04662.004879350.818 59.84729383.64560.810579400.05959.421339416.47361.43788
9439.45359.083279564.19956.705289580.61357.417469593.74456.083649629.85556.33619
9639.70354.973299662.68355.850399692.22854.176969705.35954.98829 9777.5852.85534
 9800.5652.838539807.12554.183569922.01852.157319954.84248.605079977.88444.40508
10000.9443.4026810047.0550.0263110179.57 50.784910231.7248.4252610259.0852.56243
10360.7252.5395310411.5455.4012710462.3654.3719710527.1559.3454210546.1358.22263
#Mann= 3 , 0 , 0
9292.046   0.045       09292.046   0.045       010546.13   0.045       0
#XS Ineff= 2 , 0
       09924.859        10047.19       0
Bank Sta=9292.046,10546.13
Exp/Cntr=0.3,0.1

Type RM Length L Ch R = 1 ,2273.128,159.809100,159.809100,159.809100
XS GIS Cut Line= 6
1270930.78266156619575.211372226 1271030.2844469618890.867985651
1271020.68717545618823.4579000171270991.17328653 618736.65234445
1270952.97884211618679.3606777791270730.26182827 618494.48220557
#Sta/Elev= 30
9396.21558.355819425.05556.749129441.61257.79416 9461.4855.264239471.41456.21584
9521.08655.041739550.888  55.9569564.13454.50374 9577.3855.142559733.01649.40617
9752.88450.357169855.53847.264799955.101 47.98579998.446 41.384210025.12 45.7837
10051.8144.2332510124.7145.3608310168.3343.5972310185.6645.7464510237.6444.27844
10255.9845.4521410310.36 44.847510388.8247.4498810431.4646.1144510452.7849.91739
 10474.151.5708510540.7250.3790410581.8152.5214110593.4954.7679810605.9454.34194
#Mann= 3 , 0 , 0
9396.215   0.045       09396.215   0.045       010605.94   0.045       0
#XS Ineff= 2 , 0
       09933.025        10033.52       0
Bank Sta=9396.215,10605.94
Exp/Cntr=0.3,0.1

Type RM Length L Ch R = 1 ,2113.319,159.809100,159.809100,159.809100
XS GIS Cut Line= 6
1271235.96495327619547.4162333461271164.51124528618918.937104076
1271136.99422863618825.6359573161271113.33228871  618774.8544842
1271067.56217545618719.2912333311270821.40766156618499.690538898
#Sta/Elev= 30
9440.16750.790579460.749 49.44649513.54549.349389543.24348.023049576.24148.80402
 9602.6446.605899678.53545.066089718.13245.471819777.528 42.93199879.82243.58185
9956.13440.521599972.64838.9919610015.5838.39695 10055.2 41.298710105.4340.32864
10142.24 41.054210151.7242.3238110174.6939.7044110193.9141.6545510221.7539.90545
10328.5143.1928610341.7142.5108710385.6644.3517110450.1345.64975 10464.845.05488
10482.3946.4586310548.3445.1109210574.7249.77553 10601.148.31509 10628.150.03102
#Mann= 3 , 0 , 0
9440.167  0.0681       09440.167  0.0681       0 10628.1  0.0681       0
#XS Ineff= 2 , 0
       0 9964.12        10033.26       0
Bank Sta=9440.167,10628.1
Exp/Cntr=0.3,0.1

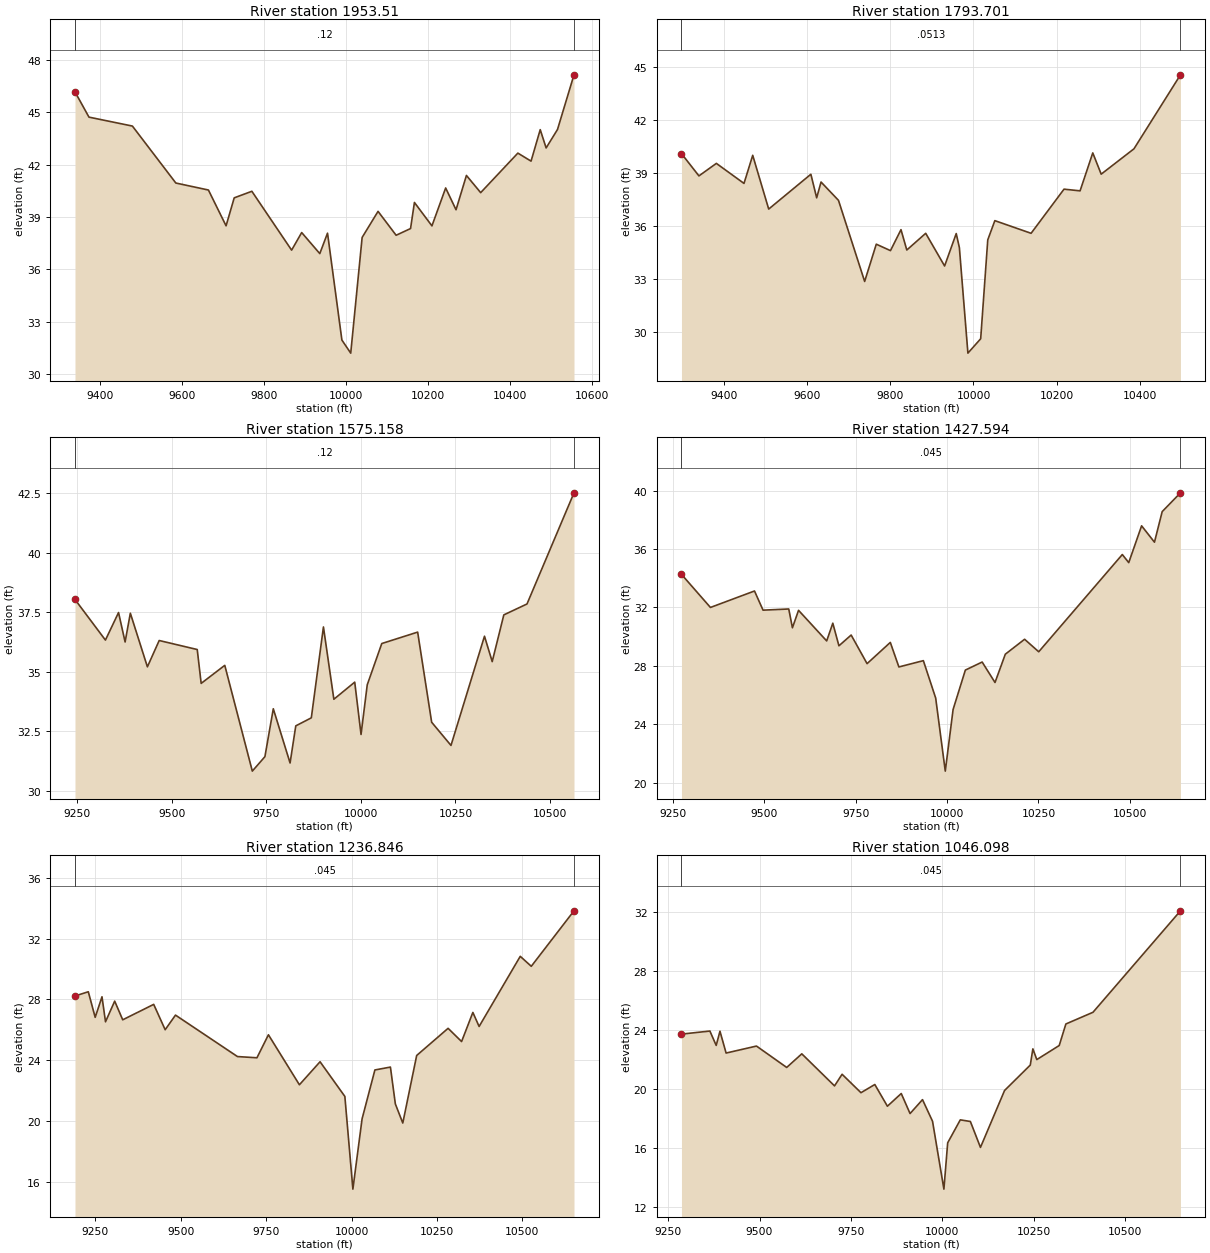
Type RM Length L Ch R = 1 , 1953.51,159.809200,159.809200,159.809200
XS GIS Cut Line= 6
1271473.81217545619550.8884555551271402.63161993619043.944011107
1271377.04553387618976.8214334991271237.74426678618872.523219883
1271086.65939769618694.9856777791270928.17849493 618533.54470557
#Sta/Elev= 30
9338.20546.169959372.314 44.72059478.33144.208579584.34740.94485 9663.8640.54483
9706.92938.493399726.80740.096259769.87640.47152  9866.937.099179891.478 38.1071
9935.649 36.90119954.527 38.07229989.61131.9474510011.1731.19878   1003937.82681
10077.8439.3215310121.9537.9520710157.1738.3365210166.6339.8312510209.3838.49025
10242.8540.6613410268.1639.4128610293.53 41.379510328.3140.3939410419.0942.65913
10451.2742.1984410473.6544.0028410488.0542.95584 10515.844.0125210556.0647.14467
#Mann= 3 , 0 , 0
9338.205    0.12       09338.205    0.12       010556.06    0.12       0
#XS Ineff= 2 , 0
       09962.278        10059.76       0
Bank Sta=9338.205,10556.06
Exp/Cntr=0.3,0.1

Type RM Length L Ch R = 1 ,1793.701,218.542400,218.542400,218.542400
XS GIS Cut Line= 6
1271630.06217548619415.4717888831271403.10306406618791.978324816
  1271273.684576618755.8815816791271220.62757918618731.803210691
1271162.78809997618690.0993558621270956.69701341618514.278212517
#Sta/Elev= 30
9298.64340.091749340.61238.830659382.50939.536939448.846 38.40589469.79539.99383
9508.201 36.95629609.45338.923729623.418 37.59099633.89338.48442 9675.7937.44892
9738.636 32.86649766.56734.972149800.64934.607459825.92235.792799839.88734.64258
9885.27635.585949930.66533.740379958.59635.572279966.12934.779419986.64328.81663
10017.32  29.62810034.3335.2161310051.3336.30224 10138.4 35.5867 10217.538.08136
10256.0637.9852410286.5440.1292210306.7638.9287910385.4440.3599110497.1544.54099
#Mann= 3 , 0 , 0
9298.643  0.0513       09298.643  0.0513       010497.15  0.0513       0
#XS Ineff= 2 , 0
       09963.467        10075.12       0
Bank Sta=9298.643,10497.15
Exp/Cntr=0.3,0.1

Type RM Length L Ch R = 1 ,1575.158,147.564000,147.564000,147.564000
XS GIS Cut Line= 6
1271678.67328659619337.3467888831271543.93659678618946.569879174
1271435.42965233618743.0108513831271461.06546497618644.003700361
1271457.56506899618580.2504347261270967.98173568618455.250434741
#Sta/Elev= 30
9243.40438.039369323.94436.332479358.648 37.4902    937636.253189389.88137.46245
9434.99635.208999466.22936.31519 9566.8735.936189577.28134.513149639.74835.27167
9712.63130.826799745.93531.433959768.13933.446829812.545 31.1693  9827.632.72828
 9868.7533.065929900.80236.884389928.40433.846979983.60134.56589 10000.332.36749
10016.72 34.454410055.1636.1882610150.1136.6679910187.1632.88107 10238.331.90745
10326.9536.4958110347.4135.4293610378.0937.3913410439.4637.8511510563.7942.52104
#Mann= 3 , 0 , 0
9243.404    0.12       09243.404    0.12       010563.79    0.12       0
#XS Ineff= 2 , 0
       09976.705        10019.78       0
Bank Sta=9243.404,10563.79
Exp/Cntr=0.3,0.1

Type RM Length L Ch R = 1 ,1427.594,190.748400,190.748400,190.748400
XS GIS Cut Line= 6
  1271779.367731619276.5829000171271645.49909675618617.142795831
1271598.33030948618591.0831576291271557.79268453 618575.62984103
1271535.87818998618562.3146808891271004.87409678618356.726129174
#Sta/Elev= 30
 9273.4134.268019352.70931.998019473.22833.125369496.66231.812539566.96531.89266
9577.00830.605069593.74731.800949670.74529.704559687.48430.918839704.22329.37007
9737.70130.107749781.22128.148739844.829  29.6039868.26327.922389935.21828.35369
9968.95425.791649995.19220.7858410016.5825.0077910050.1227.7070710096.0728.25873
10131.2526.8571110159.3928.7934410212.1729.8185210250.8728.9623110479.5435.62299
10497.1435.0693110532.3237.58939 10567.536.4695810588.6138.5617910638.6339.85002
#Mann= 3 , 0 , 0
 9273.41   0.045       0 9273.41   0.045       010638.63   0.045       0
#XS Ineff= 2 , 0
       09951.222        10065.09       0
Bank Sta=9273.41,10638.63
Exp/Cntr=0.3,0.1

Type RM Length L Ch R = 1 ,1236.846,190.748400,190.748400,190.748400
XS GIS Cut Line= 6
1271898.29134214619145.072483331  1271744.211481618433.266927779
1271595.22525814618396.4432043731271505.66301864618358.198885724
1271311.39299542618235.5285742581271109.69990095618086.499462068
#Sta/Elev= 30
9190.94228.22244 9229.8928.502159250.03126.82158 9269.95 28.17199280.24226.52718
9307.09727.886429330.59426.657739421.229 27.67339454.79726.006499485.00826.96748
9666.276 24.24339723.342 24.1625 9756.9125.674789847.544 22.38929907.96723.90234
9980.51321.62246   1000415.5312910030.8620.1449610068.4123.3617810113.8323.55271
10128.2521.1312710150.0119.8746610190.6624.31379 10282.626.0991710322.0525.22895
10355.0527.1431310373.3326.22084 10493.730.8293610525.9630.1752310650.9333.82041
#Mann= 3 , 0 , 0
9190.942   0.045       09190.942   0.045       010650.93   0.045       0
#XS Ineff= 2 , 0
       09934.968        10070.99       0
Bank Sta=9190.942,10650.93
Exp/Cntr=0.3,0.1

Type RM Length L Ch R = 1 ,1046.098,190.748400,190.748400,190.748400
XS GIS Cut Line= 6
1271967.73578656 618869.464844451271770.43926892 618248.18557483
1271533.93963957  618170.63483421271401.94539323618114.018571705
1271305.35989264618063.111552551 1271127.3968294617950.078822598
#Sta/Elev= 30
9286.44323.731629364.229 23.94029381.44122.966019391.76723.928559408.51422.44732
9491.59422.921799574.20921.471059615.51622.394539705.01620.21948 9725.67 21.0087
9777.30419.758049815.16920.313829849.59218.841159887.45819.702719911.554 18.3424
9945.57819.287779973.01717.8196710004.09 13.217110014.4316.3577910048.9117.91615
10076.4917.8049710104.0816.0470910169.9619.9078810240.2921.6317710247.3522.73074
10258.1322.0044710319.3822.9577610337.5824.4185510411.7625.2132610650.9532.09497
#Mann= 3 , 0 , 0
9286.443   0.045       09286.443   0.045       010650.95   0.045       0
#XS Ineff= 2 , 0
       09943.095         10048.5       0
Bank Sta=9286.443,10650.95
Exp/Cntr=0.3,0.1

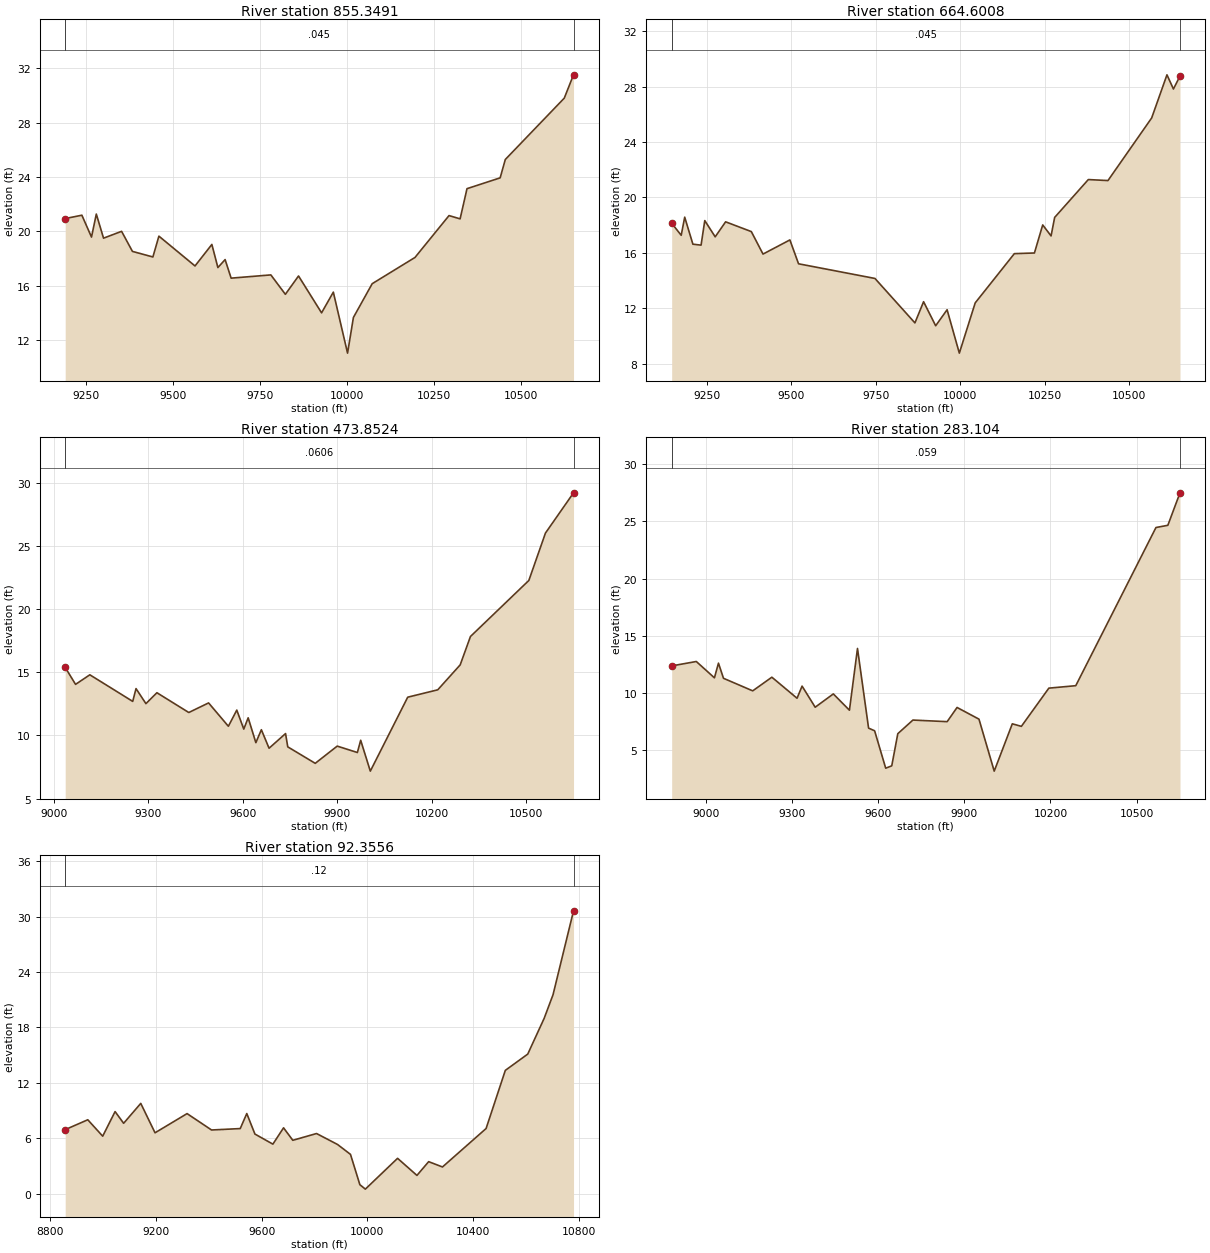
Type RM Length L Ch R = 1 ,855.3491,190.748300,190.748300,190.748300
XS GIS Cut Line= 6
1272069.73231435618765.2981777791271835.35731435618066.513455555
1271640.39329743618015.4097653931271502.47567368 617969.33263208
1271350.00084263617902.7199641911271166.47938052617798.993568763
#Sta/Elev= 30
9189.55520.933479237.47321.181269265.15619.572649278.99821.265519299.76119.49146
9351.66819.994759382.81218.51829 9441.6418.108189458.94219.640559562.75617.44588
9611.20219.030229628.50417.328639649.26717.914599666.56916.549759780.76416.78803
9822.52215.360689860.35516.709929926.59813.996329960.39415.5197710001.2911.03185
10018.13 13.656210072.1216.1409410195.1718.0729110292.9621.1524110324.8920.91356
10344.6823.1341210439.9823.9297410454.8125.2803410624.32  29.79610650.9531.51194
#Mann= 3 , 0 , 0
9189.555   0.045       09189.555   0.045       010650.95   0.045       0
#XS Ineff= 2 , 0
       09939.173        10137.72       0
Bank Sta=9189.555,10650.95
Exp/Cntr=0.3,0.1

Type RM Length L Ch R = 1 ,664.6008,190.748400,190.748400,190.748400
XS GIS Cut Line= 6
1272132.66634211 618635.08984445 1271883.2758278617893.923183426
1271762.04567632617839.0584290331271478.92640603617729.750131428
1271369.03251219617677.3026634311271225.11002833617596.014313653
#Sta/Elev= 30
9145.214  18.1399173.45917.267169183.84418.575139208.07516.624639232.30616.55583
9243.279 18.32719274.14217.155939304.99918.238449381.15417.53337 9415.7715.91145
9495.38616.931629521.04215.210859747.36814.152789865.776 10.94499891.39312.47452
9927.21410.739669961.03811.895329997.313 8.7649410044.3112.3892510160.2815.94222
10219.77 15.990210244.2618.0132710269.03 17.221510279.6718.5564910379.3821.28759
10437.5421.2151610567.0425.7333610612.3428.8444710631.4627.8192710650.9328.75634
#Mann= 3 , 0 , 0
9145.214   0.045       09145.214   0.045       010650.93   0.045       0
#XS Ineff= 2 , 0
       09933.855        10175.06       0
Bank Sta=9145.214,10650.93
Exp/Cntr=0.3,0.1

Type RM Length L Ch R = 1 ,473.8524,190.748400,190.748400,190.748400
XS GIS Cut Line= 6
 1272256.3642588618530.9231777941271954.71495324617708.440538883
1271747.31385288617645.8166455481271587.82518363617582.349618345
1271423.82653487 617499.072261811271280.85634065617412.377403885
#Sta/Elev= 30
9035.32915.383489068.211  14.0429113.63914.798869249.92612.695719260.40913.70727
 9291.8612.518339326.80513.380799428.14711.816429491.04812.575119553.94910.72924
9580.683 12.00719602.87310.504169616.85111.397199641.3139.4323719658.78510.45642
9683.2478.9910319735.66510.150049742.6639.1012439830.0177.7976669899.9079.159311
9963.9328.6533689974.4599.621129 10005.17.18083710123.9713.0283410219.4513.61199
10290.73 15.585310323.3217.8263710508.9522.2603710561.7126.0063210650.9629.19056
#Mann= 3 , 0 , 0
9035.329  0.0606       09035.329  0.0606       010650.96  0.0606       0
#XS Ineff= 2 , 0
       09944.197        10142.04       0
Bank Sta=9035.329,10650.96
Exp/Cntr=0.3,0.1

Type RM Length L Ch R = 1 , 283.104,190.748400,190.748400,190.748400
XS GIS Cut Line= 6
1272367.04134211 618517.902344451271997.70887157617539.878123373
1271827.48643485617441.9316312521271730.29860765617382.848276153
1271544.04564062617258.4946684241271390.87404588 617146.32103321
#Sta/Elev= 30
8881.58712.36874  8967.312.754219030.42511.326969044.45312.609169061.98811.28645
 9163.6910.189049230.323 11.38169317.9979.5430269335.53210.603089381.1238.759024
9444.2489.919742 9500.368.4982479528.41513.892999566.9926.9316729588.0346.698664
9626.6113.4294049647.652 3.635219668.6946.4436129721.2997.6354179840.5367.496066
9874.9938.7371599951.2577.71566110004.313.17276410067.297.30740510098.887.086589
 10194.510.4256310288.1910.6399210567.3424.4645210608.6724.6566810650.9727.49592
#Mann= 3 , 0 , 0
8881.587   0.059       08881.587   0.059       010650.97   0.059       0
#XS Ineff= 2 , 0
       0 9934.87        10068.74       0
Bank Sta=8881.587,10650.97
Exp/Cntr=0.3,0.1

Type RM Length L Ch R = 1 , 92.3556,0.000000,0.000000,0.000000
XS GIS Cut Line= 6
1272938.98868012618066.8389763981272580.91576341617882.377170846
1272437.68659675617780.3806430551272324.83937457617680.554254174
1271873.19524479617137.8252637981271478.48520786616853.731337517
#Sta/Elev= 30
8856.7116.945639 8942.178.0133258998.639 6.236779045.468 8.899729077.8717.633395
9142.6769.7851819196.6816.6030439317.9428.6793599410.5796.9069689519.162 7.06031
 9543.928.686891 9574.746.4668939642.739 5.377479683.0627.1415419718.0885.791784
9807.8566.5246479887.3285.3416319936.3954.2695119971.8810.9907119992.6650.510109
10114.633.842302 10187.91.99432910232.233.48101710284.512.90669210449.617.067301
10522.3713.3557610607.2615.1185110669.3218.9797410703.0221.5448910780.5230.61488
#Mann= 3 , 0 , 0
8856.711    0.12       08856.711    0.12       010780.52    0.12       0
#XS Ineff= 2 , 0
       09893.093        10132.27       0
Bank Sta=8856.711,10780.52
Exp/Cntr=0.3,0.1